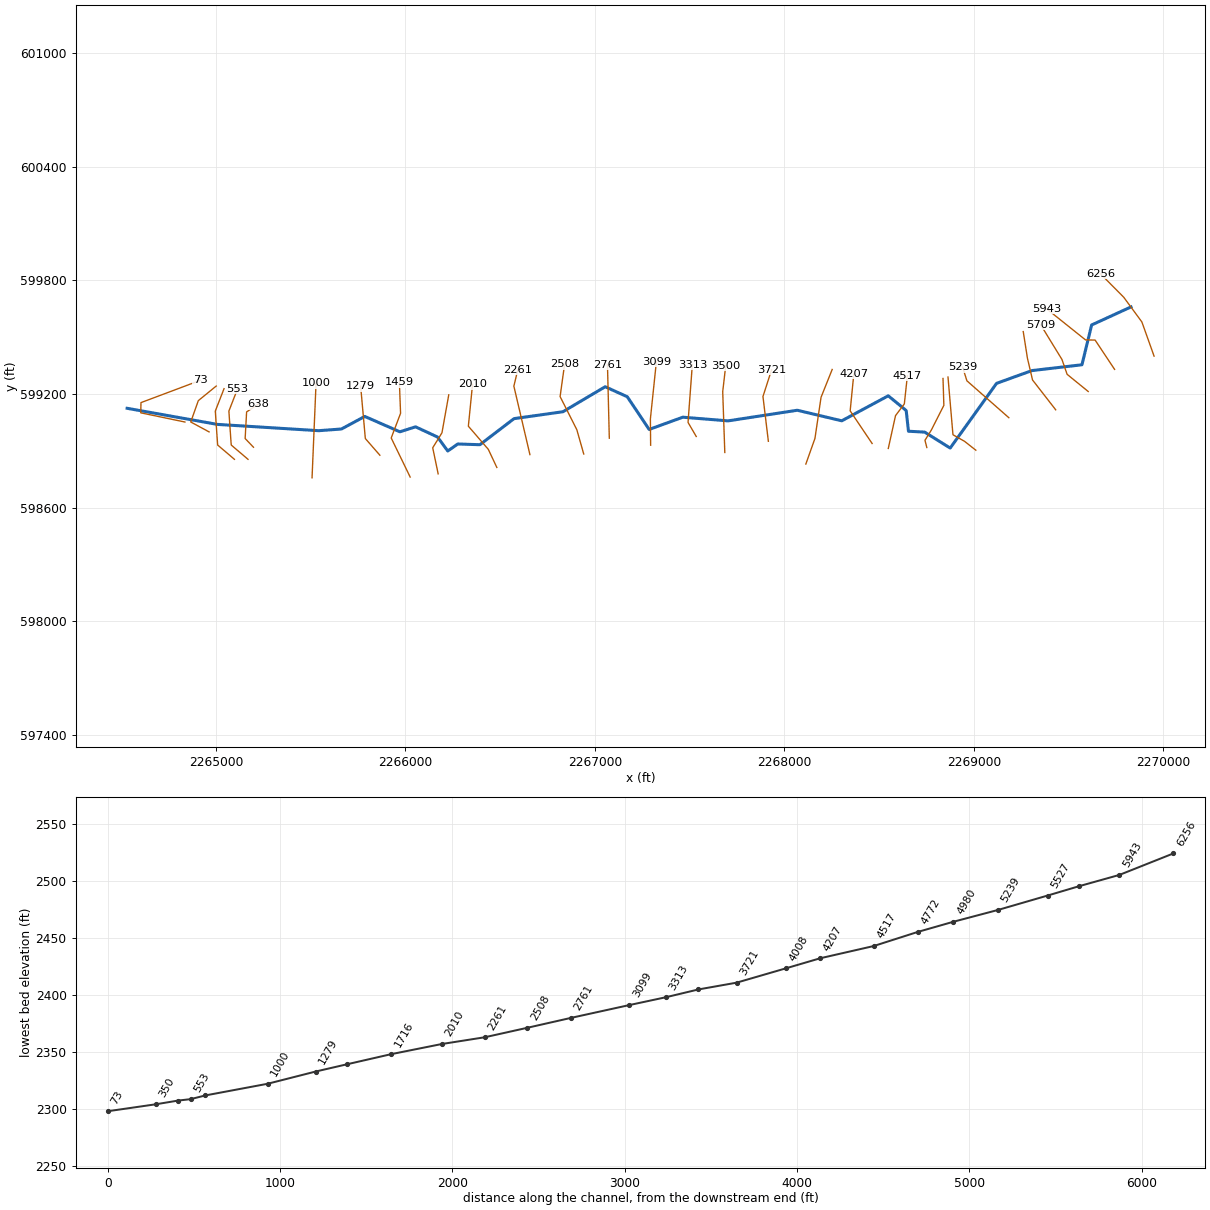
--- BIGBR.prj (project) ---

Proj Title=BIGBR
Current Plan=p01
Default Exp/Contr=0,0
English Units
Geom File=g01
Flow File=f01
Plan File=p01
BEGIN DESCRIPTION:
----------MODEL BY WOOD PLC 2022----------
AFH study
Randolph County, WV
HEC-RAS Version: RAS 6.2
Vertical Datum: NAVD88
Projection: NAD 1983 StatePlane West Virginia S FIPS 4702 (US Feet)
Terrain: 1-meter LIDAR (FEMA Region III 3DEP collected 2016-2018)
Land Use: 2019 NLCD
Hydrologic Method:
WV SIR2010-5033 regression equations
Additional Model Notes:
None
END DESCRIPTION:
DSS Export Rating Curves= 0
DSS Export Rating Curve Sorted= 0
DSS Export Volume Flow Curves= 0
DXF OffsetX= 0
DXF OffsetY= 0
DXF ScaleX= 0
DXF ScaleY= 0

--- BIGBR.p01 (plan) ---

Plan Title=Floodplain
Program Version=6.20
Short Identifier=Floodplain
Geom File=g01
Flow File=f01
Subcritical Flow
K Sum by GR= 0
Std Step Tol= 0.01
Critical Tol= 0.01
Num of Std Step Trials= 20
Max Error Tol= 0.3
Flow Tol Ratio= 0.001
Split Flow NTrial= 30
Split Flow Tol= 0.02
Split Flow Ratio= 0.02
Log Output Level= 0
Friction Slope Method= 1
Unsteady Friction Slope Method= 2
Unsteady Bridges Friction Slope Method= 1
Parabolic Critical Depth
Global Vel Dist= 0 , 0 , 0
Global Log Level= 0
CheckData=True
Encroach Param=-1 ,0,0, 0
Mapping Interval=1HOUR
Computation Time Step Use Courant=        0
Computation Time Step Use Time Series=    0
Computation Time Step Count To Double=0
Computation Time Step Max Doubling=0
Computation Time Step Max Halving=0
Computation Time Step Residence Courant=0
Run HTab= 0
Run UNet= 0
Run Sediment= 0
Run PostProcess= 0
Run WQNet= 0
Run RASMapper=-1
UNET Theta= 0
UNET Theta Warmup= 0
UNET ZTol= 0
UNET ZSATol= 0
UNET MxIter= 0
UNET Max Iter WO Improvement= 0
UNET MaxInSteps= 0
UNET DtIC= 0
UNET DtMin= 0
UNET MaxCRTS= 0
UNET WFStab= 0
UNET SFStab= 0
UNET WFX= 1
UNET SFX= 1
UNET Gravity=32.174
UNET 1D Methodology=Finite Difference
UNET DSS MLevel= 1
UNET Pardiso=0
UNET DZMax Abort= 0
UNET Use Existing IB Tables= 0
UNET Froude Reduction=False
UNET Froude Limit= 0
UNET Froude Power= 0
UNET D1 Cores= 0
UNET WindReference=Eulerian
UNET WindDragFormulation=Hsu (1988)
UNET D2 Coriolis=0
UNET D2 Cores= 0
UNET D2 Theta= 1
UNET D2 Theta Warmup= 1
UNET D2 Z Tol= 0.01
UNET D2 Volume Tol= 0.01
UNET D2 Max Iterations= 20
UNET D2 Equation= 0
UNET D2 RampUpFraction=0.1
UNET D2 TimeSlices= 1
UNET D2 Turbulence Formulation=Non-Conservative (original)
UNET D2 Eddy Viscosity=0.3
UNET D2 Transverse Eddy Viscosity=0.1
UNET D2 Smagorinsky Mixing=0
UNET D2 BCVolumeCheck=0
UNET D2 Cores=0
UNET D2 SolverType=PARDISO (Direct)
UNET D2 Minimum Iterations= 2147483647
UNET D2 Maximum Iterations= 2147483647
UNET D2 Restart Number= 10
UNET D2 Relaxation Coeff=1.3
UNET D2 SOR Precondition Iterations= 10
UNET D2 ILUT Maximum Fill= 8
UNET D2 ILUT Tolerance=1E-08
UNET D1D2 MaxIter= 0
UNET D1D2 ZTol=0.01
UNET D1D2 QTol=0.1
UNET D1D2 MinQTol=1
Write IC File= 0
Write IC File at Fixed DateTime=0
Write IC File at Sim End=0
Echo Input=False
Echo Parameters=False
Echo Output=False
Write Detailed= 0
HDF Write Warmup=0
HDF Write Time Slices=0
HDF Flush=0
HDF Compression= 1
HDF Chunk Size= 1
HDF Spatial Parts= 1
HDF Use Max Rows=0
HDF Fixed Rows= 1
Calibration Method= 0
Calibration Iterations= 20
Calibration Max Change=0.05
Calibration Tolerance=0.2
Calibration Maximum=1.5
Calibration Minimum=0.5
Calibration Optimization Method= 1
WQ AD Non Conservative
WQ ULTIMATE=-1
WQ Max Comp Step=1HOUR
WQ Output Interval=15MIN
WQ Output Selected Increments= 0
WQ Output face flow=0
WQ Output face velocity=0
WQ Output face area=0
WQ Output face dispersion=0
WQ Output cell volume=0
WQ Output cell surface area=0
WQ Output cell continuity=0
WQ Output cumulative cell continuity=0
WQ Output face conc=0
WQ Output face dconc_dx=0
WQ Output face courant=0
WQ Output face peclet=0
WQ Output face adv mass=0
WQ Output face disp mass=0
WQ Output cell mass=0
WQ Output cell source sink temp=0
WQ Output nsm pathways=0
WQ Output nsm derived pathways=0
WQ Create Restart=0
WQ Fixed Restart=0
WQ System Summary=0
WQ Write To DSS=0
Sorting and Armoring Iterations= 10
XS Update Threshold= 0.02
Bed Roughness Predictor= 0
Hydraulics Update Threshold= 0.02
Energy Slope Method= 1
Volume Change Method= 1
Sediment Retention Method= 0
Sediment TS Multiplier= 1
Warm Up Method= 0
XS Weighting Method= 0
Number of US Weighted Cross Sections= 1
Number of DS Weighted Cross Sections= 1
Upstream XS Weight=0
Main XS Weight=1
Downstream XS Weight=0
Number of DS XS's Weighted with US Boundary= 1
Upstream Boundary Weight= 1
Weight of XSs Associated with US Boundary= 0
Number of US XS's Weighted with DS Boundary= 1
Downstream Boundary Weight= 0.5
Weight of XSs Associated with DS Boundary= 0.5
Percentile Method= 0
Sediment Output Level= 3
Mass or Volume Output= 0
Output Increment Type= 1
Profile and TS Output Increment= 1
Transport Output Increment 1
XS Output Flag= 0
XS Output Increment= 10
Read HDF5 Sediment Hotstart= 0
Sediment Hotstart Type= 0
Write Gradation File= 0
Read Gradation Hotstart= 0
Write HDF5 File= 1
Write Binary Output= 1
Write DSS Sediment File= 0
DSS Sediment Output Type= 1
SV Curve= 0
Specific Gage Flag= 0
Subcell Erosion Methods= 0
Subcell Deposition Methods= 0
Advection Scheme= 1
Matrix Solver= 0
Implicit Weighting Factor= 1
Maximum Outer Loop Convergence Iterations= 5
Convergence Maximum Absolute= 0.001
Convergence RMSE= 0.0001
Grain Fractions Max Abs Error= 0.001
Max Subgrid Regions= 1
Max Subgrid Length Scale= 3.402823E+38
Initial Layer Thickness= 3.402823E+38
Min Layer Thickness= 3.402823E+38
Max Layer Thickness= 3.402823E+38
Number of Layers= 5

--- BIGBR.f01 (steady flow) ---

Flow Title=Flow
Program Version=6.20
Number of Profiles= 1
Profile Names=P100yr
River Rch & RM=BIGBR,Main,6256
     559
River Rch & RM=BIGBR,Main,3721
     623
Boundary for River Rch & Prof#=BIGBR,Main            , 1
Up Type= 0
Dn Type= 3
Dn Slope=0.02559
DSS Import GetInterval= 0
DSS Import GetPeak= 0
DSS Import FillOption= 0

--- BIGBR.g01 (geometry) ---

Geom Title=Geometry
Program Version=6.20

River Reach=BIGBR           ,Main
Reach XY= 30
2269828.64566467599659.401306926     2269620.941      599564.202
     2269569.726      599354.133     2269305.886      599323.476
     2269119.205      599256.043     2268874.484      598914.509
      2268739.78      598998.773     2268654.376      599003.425
2268642.27964417599112.7068382572268547.67831445599190.391553972
     2268302.365599058.407727377     2268067.871 599114.16244548
      2267702.65      599058.135     2267463.401      599077.486
      2267286.03      599012.795     2267170.508      599185.444
     2267054.026      599238.159     2266831.234      599106.437
     2266573.118       599069.95     2266392.842      598932.292
     2266276.177      598936.152     2266223.205       598899.12
     2266169.272      598972.871     2266053.244      599026.701
      2265970.43      599000.382     2265785.536      599081.551
      2265662.29      599015.219     2265542.808      599006.298
     2265007.217      599039.563     2264531.427      599124.465

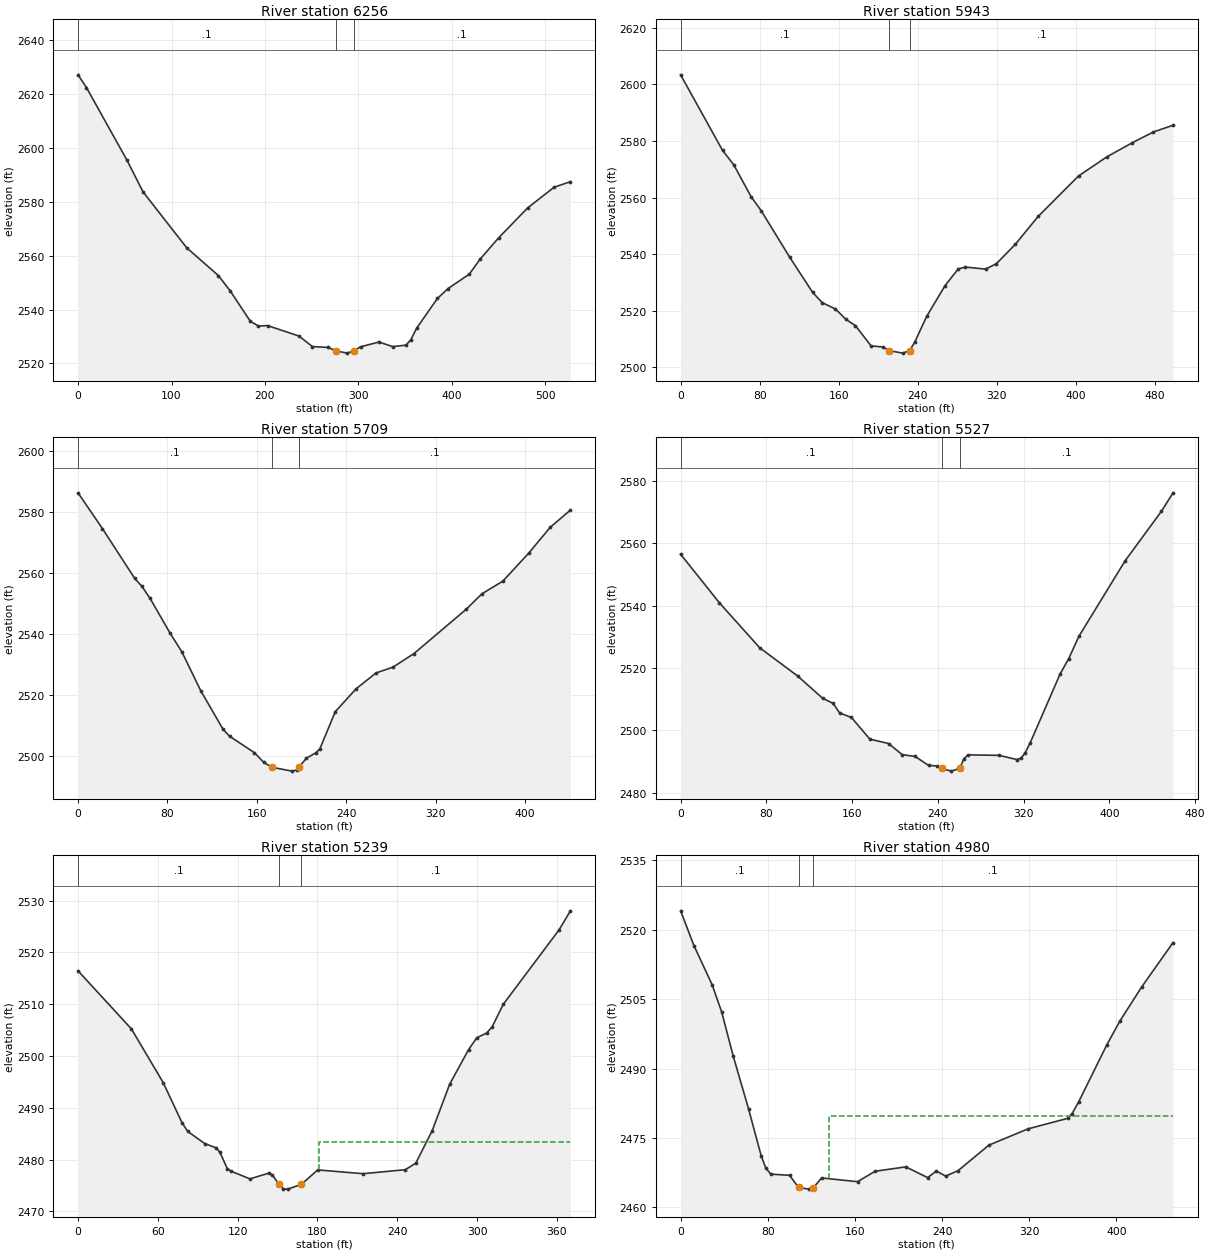
Type RM Length L Ch R = 1 ,6256    ,302.9,313.8,322.4
XS GIS Cut Line= 4
2269950.29568256599399.7506215442269886.04267693599579.869702877
2269790.18983248599710.482370043  2269668.003789599833.721741481
#Sta/Elev= 30
       0 2627.09       9 2622.38    52.5 2595.33    69.5 2583.68   116.2 2562.94
   150.2 2552.59   162.9 2546.89   184.3 2535.66   192.9 2533.88   202.8 2534.04
   236.4 2530.17   250.7 2526.27   267.3 2525.94  276.222524.661   287.9 2523.83
  295.172524.663   302.2 2526.18   321.9 2527.94   336.7 2526.25   350.9 2526.79
   356.1 2528.83   362.2 2533.04   384.5 2544.13   395.9  2547.8   418.6 2553.13
   430.1 2558.67   449.9 2566.58   481.1 2577.74   509.3 2585.37   526.8 2587.46
#Mann= 3 ,-1,0
       0      .1       0  276.22    .045       0  295.17      .1       0
Bank Sta=276.22,295.17
XS Rating Curve= 0 ,0
Exp/Cntr(USF)=0,0
Exp/Cntr=0.3,0.1

Type RM Length L Ch R = 1 ,5943    ,247.8,233.9,221.5
XS GIS Cut Line= 4
2269741.93075467599329.8560092732269639.18056273599484.537465667
2269588.73110404599485.2285541422269383.99739635599648.862145047
#Sta/Elev= 30
       0  2603.4    42.4 2576.69    53.8 2571.56    71.2 2560.36    81.6  2555.3
   110.4 2538.87   133.6 2526.45   143.2 2522.84   156.6 2520.58   167.3 2516.91
   176.9 2514.68   192.7 2507.53   204.7 2507.14  211.19 2505.84   224.6 2504.97
  231.712505.839   236.9 2508.86   248.9 2517.94   267.6 2528.87   280.9 2534.76
   288.1  2535.4   308.6 2534.69   319.4 2536.57   338.6 2543.43   361.7 2553.31
   402.6 2567.63   431.4 2574.42   457.1  2579.4   478.4 2583.19   498.2 2585.56
#Mann= 3 ,-1,0
       0      .1       0  211.19    .045       0  231.71      .1       0
Bank Sta=211.19,231.71
XS Rating Curve= 0 ,0
Exp/Cntr(USF)=0,0
Exp/Cntr=0.3,0.1

Type RM Length L Ch R = 1 ,5709    ,185.2,182,181.5
XS GIS Cut Line= 4
2269602.76933239599213.1621669462269491.45874882599303.763804737
2269464.27825748599382.0695059712269352.32051935599564.567090663
#Sta/Elev= 30
       0 2586.35    21.8 2574.64    50.7 2558.28    57.1 2555.71    64.4 2551.77
    82.4 2540.28    92.8 2534.27   109.9 2521.37   129.8 2508.78   135.5 2506.55
   157.7 2501.16   166.2 2497.95  173.52 2496.34   191.6 2495.09   195.8  2495.5
   197.5 2496.33   204.3 2499.33   212.8  2501.1   216.4 2502.45   230.1 2514.57
   248.8 2522.11   266.6 2527.29   281.7 2529.18   300.5 2533.63   347.4 2548.21
   361.5 2553.29     380 2557.37   403.3 2566.62   422.5 2575.08   440.5 2580.68
#Mann= 3 ,-1,0
       0      .1       0  173.52    .045       0   197.5      .1       0
Bank Sta=173.52,197.5
XS Rating Curve= 0 ,0
Exp/Cntr(USF)=0,0
Exp/Cntr=0.3,0.1

Type RM Length L Ch R = 1 ,5527    ,284.5,288,294
XS GIS Cut Line= 4
2269431.17636027599116.5697025652269309.01460385599273.903794503
2269282.06215332 599388.624481392269259.92122529599529.230624561
#Sta/Elev= 30
       0  2556.5    36.2 2540.91    73.8 2526.49   109.2 2517.43   132.4 2510.32
   142.3 2508.64   148.4 2505.57   159.4 2504.13   176.5 2497.19     194 2495.78
   206.7 2492.21   218.6 2491.64   231.3 2488.78   239.5 2488.56  243.422487.819
   252.5 2486.92  260.492487.814   264.2 2490.86   268.3 2492.14   297.1 2491.98
   313.5 2490.65   317.6 2491.06   321.6 2492.88   326.2 2496.05     354 2518.04
   362.1 2523.01   371.6 2530.18   414.8 2554.44   448.6 2570.28   459.4  2576.2
#Mann= 3 ,-1,0
       0      .1       0  243.42    .045       0  260.49      .1       0
Bank Sta=243.42,260.49
XS Rating Curve= 0 ,0
Exp/Cntr(USF)=0,0
Exp/Cntr=0.3,0.1

Type RM Length L Ch R = 1 ,5239    ,257.1,258.6,260
XS GIS Cut Line= 3
2269184.06033489599074.6710920382268962.73347685599269.464613288
2268940.08306741599341.298768964
#Sta/Elev= 30
       0 2516.45    40.1 2505.24      64 2494.88    78.2  2487.1    82.5 2485.43
    95.2  2483.1   103.7 2482.28   106.6 2481.45   112.2 2478.26   115.1 2477.75
   129.2 2476.27   143.7  2477.4   146.2 2477.02     1512475.209   154.4 2474.32
   157.6 2474.29  167.85  2475.2   180.2    2478   214.3 2477.27     246 2478.04
   253.9 2479.29   266.3  2485.6   279.4 2494.55   293.6 2501.23   299.8 2503.53
   307.1 2504.42   311.3 2505.61   319.7 2509.99   361.6 2524.35   370.2 2528.04
#Mann= 3 ,-1,0
       0      .1       0     151    .045       0  167.85      .1       0
#XS Ineff= 2 , 0
                          180.92         2483.37
Permanent Ineff=
       F       F
Bank Sta=151,167.85
XS Rating Curve= 0 ,0
Exp/Cntr(USF)=0,0
Exp/Cntr=0.3,0.1

Type RM Length L Ch R = 1 ,4980    ,220.2,208.5,196.6
XS GIS Cut Line= 4
2269009.76975445598903.2998359942268950.45553597598950.021442482
2268889.09816244598984.8978974852268862.89130509599289.547878593
#Sta/Elev= 30
       0 2524.07    12.2 2516.58    28.9 2508.12    37.7 2502.21    48.3 2492.68
    62.3 2481.33    74.1 2471.03    78.1 2468.55    82.7  2467.2     100 2466.94
   108.22464.329   117.6 2463.96   121.92464.291   129.4 2466.37   162.4 2465.57
   178.5 2467.82   206.6 2468.77   226.7 2466.45   234.7 2467.86   243.3 2466.77
   254.8 2467.98   282.9 2473.46     319 2476.99   355.1 2479.24   359.1  2480.2
   365.3  2482.8   391.2 2495.15   403.3 2500.33   423.4 2507.72   451.9 2517.21
#Mann= 3 ,-1,0
       0      .1       0   108.2    .045       0   121.9      .1       0
#XS Ineff= 2 , 0
                          135.74         2479.67
Permanent Ineff=
       F       F
Bank Sta=108.2,121.9
XS Rating Curve= 0 ,0
Exp/Cntr(USF)=0,0
Exp/Cntr=0.3,0.1

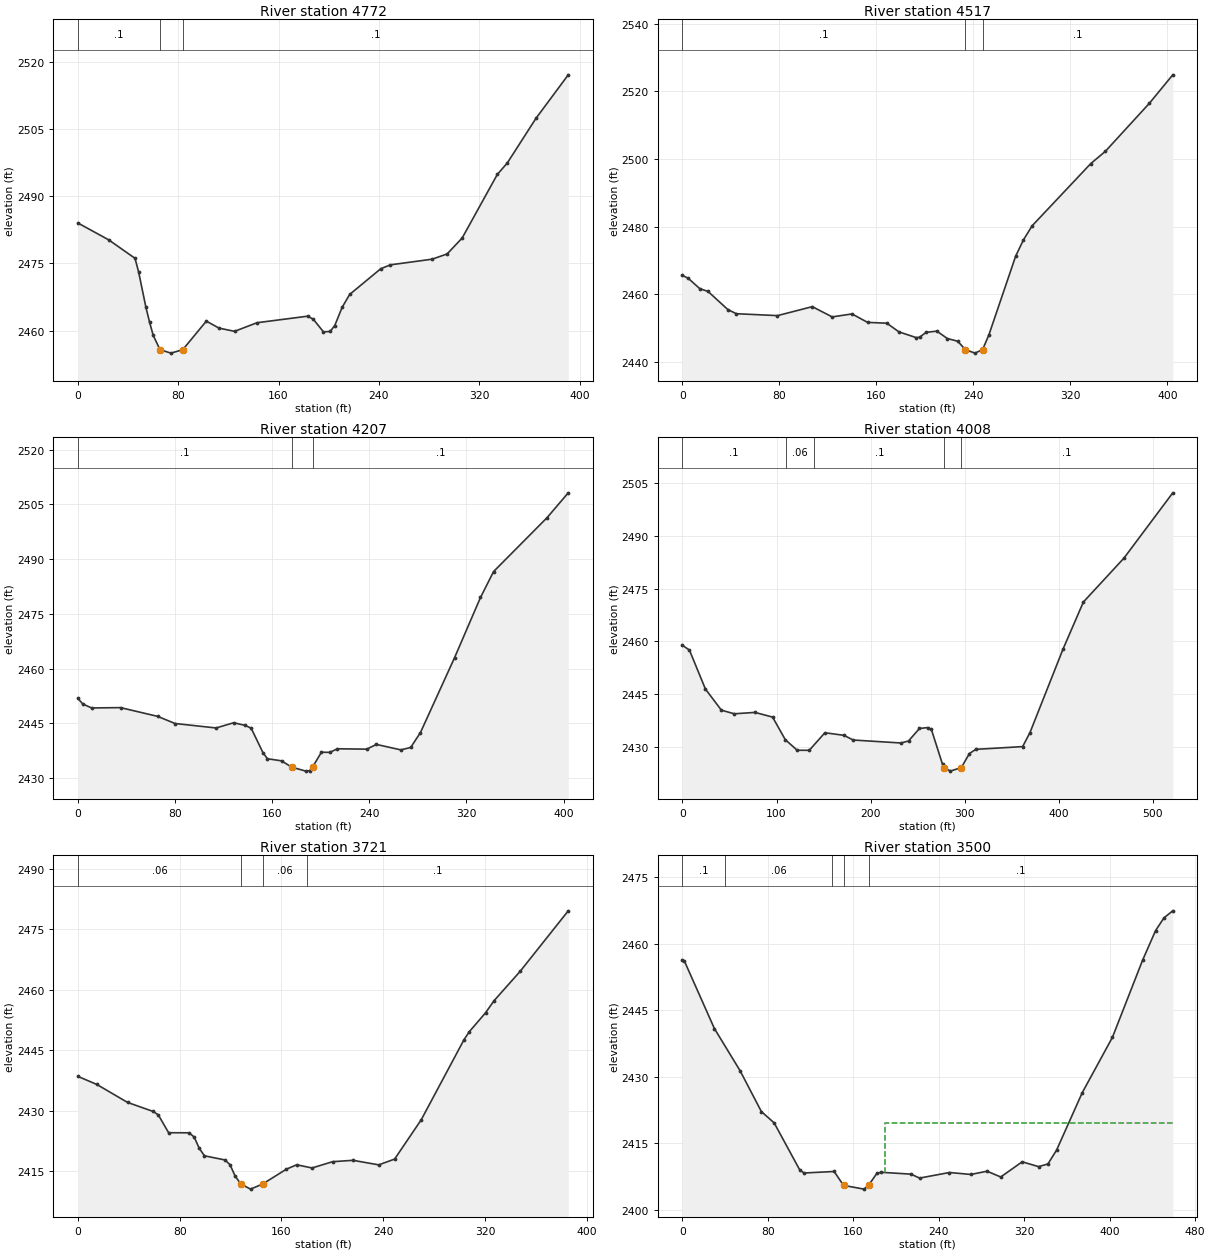
Type RM Length L Ch R = 1 ,4772    ,255.2,254.8,252.5
XS GIS Cut Line= 5
2268751.11393716598917.4125350152268741.40661882598955.594653798
2268775.05865572599009.9556364732268841.06842039599140.033702158
 2268836.5383385599281.760549845
#Sta/Elev= 30
       0 2483.98    24.5 2480.23    45.5 2476.11    48.4 2473.06    54.2  2465.2
    57.1 2461.89      60 2458.95   65.41 2455.74    74.2 2454.96    83.6 2455.73
   102.4  2462.1   112.5 2460.54   124.9 2459.82   142.8 2461.74   183.2  2463.2
   187.7 2462.52   195.8  2459.7   201.1 2459.79   204.8 2461.11   210.7 2465.18
   216.7 2468.05   241.5 2473.79   249.2 2474.65   282.4 2475.91   294.4 2477.08
   306.4 2480.63   334.4  2494.8   342.4 2497.37   365.2  2507.3     391 2517.03
#Mann= 3 ,-1,0
       0      .1       0   65.41    .045       0    83.6      .1       0
Bank Sta=65.41,83.6
XS Rating Curve= 0 ,0
Exp/Cntr(USF)=0,0
Exp/Cntr=0.3,0.1

Type RM Length L Ch R = 1 ,4517    ,299.7,310.1,318.5
XS GIS Cut Line= 4
2268547.78674672598912.5722890922268586.03678759599085.900774965
2268632.48855067599147.5204606852268648.60791731599296.496094646
#Sta/Elev= 30
       0 2465.62     4.7 2464.78    14.3  2461.7    21.1 2460.88    37.5  2455.5
    44.5 2454.29    78.4 2453.73   107.1 2456.38   123.5 2453.35   139.9 2454.23
   152.7 2451.73   168.6 2451.49   178.5 2448.94   192.8 2447.23   195.6 2447.32
     201 2448.79   209.9 2449.14   218.5 2446.96   227.1 2446.16  233.362443.688
   241.3 2442.64  247.622443.692   252.8 2448.04   274.9 2471.33   281.3 2476.12
   288.5  2480.3   336.8 2498.66   348.9 2502.31   385.1 2516.47   404.5 2524.92
#Mann= 3 ,-1,0
       0      .1       0  233.36    .045       0  247.62      .1       0
Bank Sta=233.36,247.62
XS Rating Curve= 0 ,0
Exp/Cntr(USF)=0,0
Exp/Cntr=0.3,0.1

Type RM Length L Ch R = 1 ,4207    ,206.8,199.1,194.2
XS GIS Cut Line= 3
2268462.48300534598938.7686353512268346.64233988599110.911747154
2268366.05697655599306.352422959
#Sta/Elev= 30
       0 2451.83     4.1  2450.3    11.3 2449.24    35.1 2449.33    65.6 2446.94
      80 2444.98   113.8 2443.76   128.3 2445.19   137.9 2444.45   142.7  2443.7
   152.4 2437.01   156.1 2435.33   167.7 2434.76   176.1 2433.03   187.8 2431.94
   190.9 2432.07  193.32 2433.08   200.6 2437.12   207.5 2437.08   213.8 2438.06
   237.9 2437.96   245.9 2439.25     266 2437.76   274.1 2438.42   282.1 2442.47
   310.3 2463.04   331.6 2479.49   342.4 2486.59   386.5 2501.37   403.9 2508.15
#Mann= 3 ,-1,0
       0      .1       0   176.1    .045       0  193.32      .1       0
Bank Sta=176.1,193.32
XS Rating Curve= 0 ,0
Exp/Cntr(USF)=0,0
Exp/Cntr=0.3,0.1

Type RM Length L Ch R = 1 ,4008    ,284.2,286.3,289
XS GIS Cut Line= 4
2268112.75548037  598830.18512092268160.81039741598965.386131668
2268193.04223301599182.4770244342268251.76005765599329.379442248
#Sta/Elev= 30
       0 2458.87     7.4 2457.52    24.4 2446.45    41.4 2440.43    55.1 2439.41
    77.1  2439.8    95.8 2438.47   109.3 2432.05     122 2429.04   134.8 2429.03
   151.4 2434.02   171.6 2433.29   181.5 2431.95   232.2 2431.11   240.3 2431.68
   251.9 2435.23   260.5 2435.49   264.6 2434.95   276.5    2425   278.52424.139
   284.8 2423.11  296.45 2424.14     305 2428.09   311.8  2429.3   361.6 2430.08
   369.4 2434.07   404.6 2457.84   426.2 2471.19   469.3 2483.66   521.2 2502.22
#Mann= 5 ,-1,0
       0      .1       0     110     .06       0     140      .1       0
   278.5    .045       0  296.45      .1       0
Bank Sta=278.5,296.45
XS Rating Curve= 0 ,0
Exp/Cntr(USF)=0,0
Exp/Cntr=0.3,0.1

Type RM Length L Ch R = 1 ,3721    ,222.8,221.2,220.6
XS GIS Cut Line= 3
2267914.99025126598950.4174173532267886.51545081599186.628830165
2267931.81626971 599327.06136874
#Sta/Elev= 30
       0 2438.52    14.9 2436.51      39 2432.06    59.2 2429.81    63.2 2428.96
    71.3 2424.54    87.4 2424.52    91.4 2423.46    95.4 2420.66    99.5 2418.81
   115.6 2417.78   119.6  2416.6   123.6 2413.76   128.2  2411.8   135.7 2410.54
   145.2 2411.81   163.9 2415.49     172 2416.58   184.1 2415.79   200.2 2417.35
   216.3 2417.69   236.5 2416.56     249    2418   269.9 2427.75   303.6 2447.66
   307.8 2449.65   320.5 2454.31   327.1 2457.28   347.6 2464.56   385.5 2479.61
#Mann= 4 ,-1,0
       0     .06       0   128.2    .045       0   145.2     .06       0
     180      .1       0
Bank Sta=128.2,145.2
XS Rating Curve= 0 ,0
Exp/Cntr(USF)=0,0
Exp/Cntr=0.3,0.1

Type RM Length L Ch R = 1 ,3500    ,189.3,187.4,186.5
XS GIS Cut Line= 3
 2267685.1671694598891.3091168652267674.14239389599212.574462808
2267690.03382853599349.320490916
#Sta/Elev= 30
       0 2456.24     1.9    2456    29.9 2440.83    53.9 2431.34    73.9  2422.1
    85.9 2419.54   109.9  2408.9   113.9 2408.25     142 2408.59  150.832405.456
     170 2404.61   174.22405.457     182 2408.16     186 2408.41     214 2407.99
     222  2407.1     250 2408.36     270 2407.92   285.2 2408.65     298 2407.35
   318.1 2410.77   333.5 2409.68   342.2 2410.29   350.3 2413.41   374.3 2426.35
   402.6 2438.85   430.8 2456.22     443 2462.93   450.9 2465.81   459.1 2467.38
#Mann= 5 ,-1,0
       0      .1       0      40     .06       0     140      .1       0
  150.83    .045       0   174.2      .1       0
#XS Ineff= 2 , 0
                          189.89         2419.43
Permanent Ineff=
       F       F
Bank Sta=150.83,174.2
XS Rating Curve= 0 ,0
Exp/Cntr(USF)=0,0
Exp/Cntr=0.3,0.1

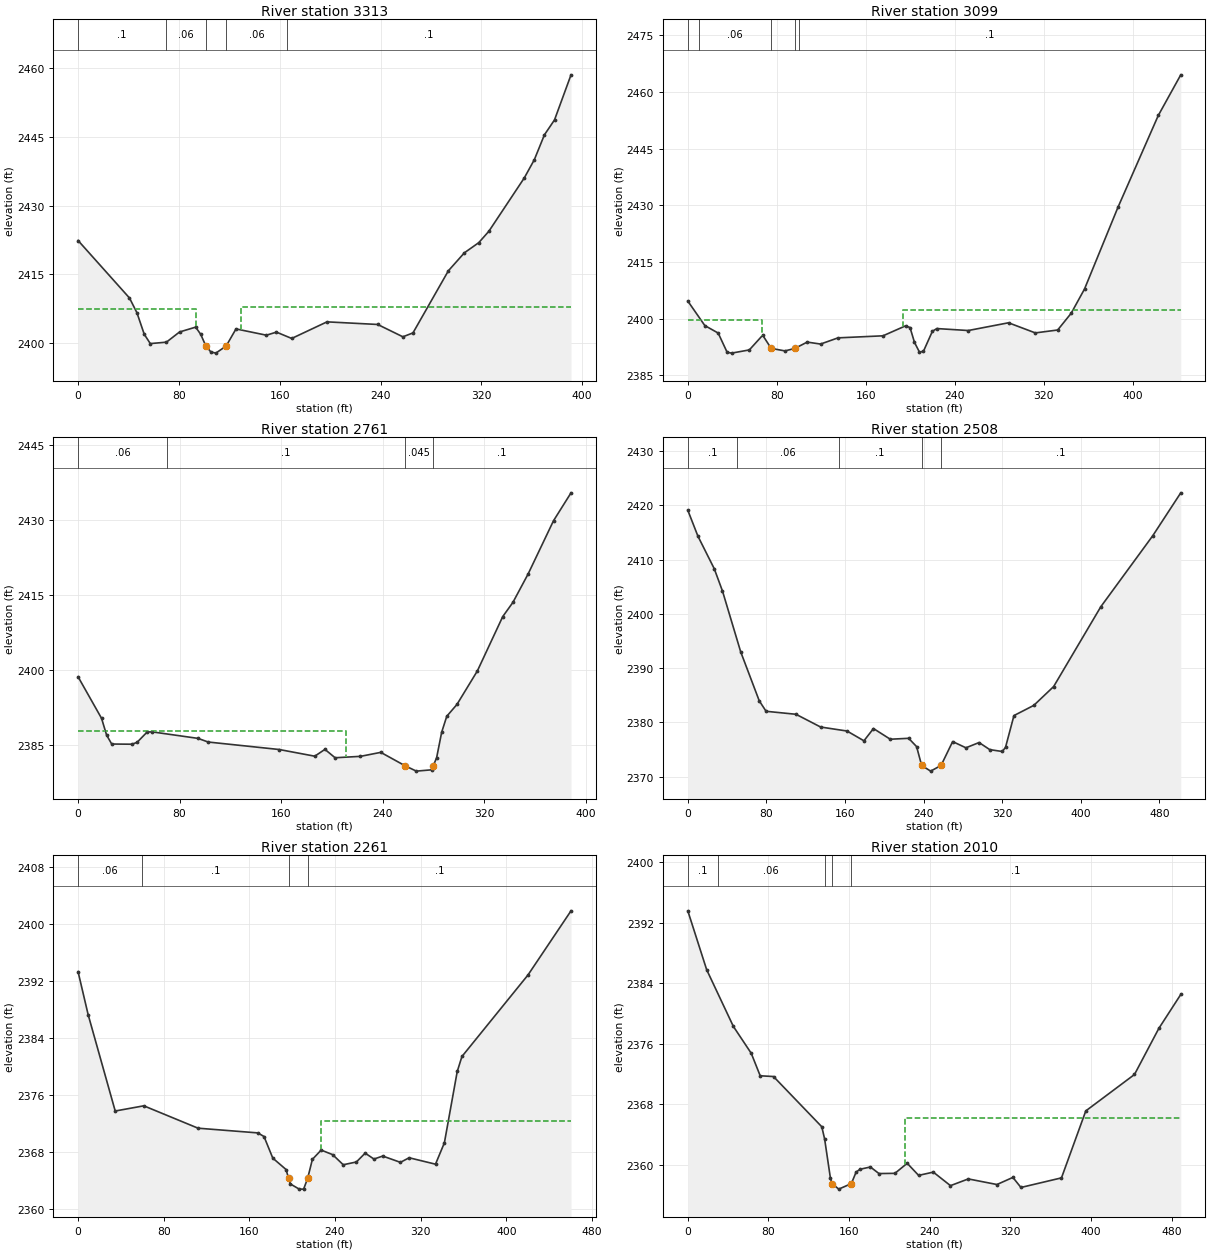
Type RM Length L Ch R = 1 ,3313    ,212,214,211.6
XS GIS Cut Line= 3
2267534.46337254598975.6564450232267491.10401731599050.079218923
2267513.75442676599354.241860077
#Sta/Elev= 30
       0 2422.39    40.8 2409.85    46.7 2406.64    52.5 2401.95    57.3 2399.91
    70.1 2400.22    80.5 2402.44    93.3  2403.5    97.3 2401.93   101.3 2399.44
   105.3  2398.1   109.3 2397.83  117.47 2399.37   125.3 2403.11   149.4 2401.74
   157.4 2402.41   169.5 2401.03   197.5 2404.65   237.7 2404.08   257.7 2401.39
   265.7 2402.24   293.8 2415.79   306.5 2419.71   317.9 2421.92   325.9  2424.4
     354 2436.03     362 2440.02     370 2445.44     378 2448.69   391.1 2458.52
#Mann= 5 ,-1,0
       0      .1       0      70     .06       0   101.3    .045       0
  117.47     .06       0  166.13      .1       0
#XS Ineff= 2 , 0
           93.68 2407.52  128.87         2407.97
Permanent Ineff=
       F       F
Bank Sta=101.3,117.47
XS Rating Curve= 0 ,0
Exp/Cntr(USF)=0,0
Exp/Cntr=0.3,0.1

Type RM Length L Ch R = 1 ,3099    ,330.6,337.6,332.3
XS GIS Cut Line= 3
 2267293.8140044598929.8373895742267292.51969529599068.975619038
2267324.23026851599371.196796525
#Sta/Elev= 30
       0 2404.68    15.3 2398.19    27.3 2396.21    35.3 2391.15    39.3  2390.9
    55.3 2391.75    67.3 2395.64   74.92 2392.15    87.3 2391.49    96.1 2392.13
   107.3 2393.82   119.3  2393.3     135 2394.94   175.4 2395.48   195.7 2398.12
   199.7 2397.67   203.7 2393.75   208.2 2391.15   211.8 2391.41   219.8 2396.68
   223.8  2397.4     252 2396.88   288.2 2398.93   312.3 2396.25   332.4 2397.02
   344.5 2401.44   356.5 2407.86   386.5 2429.44   422.8 2453.78     443 2464.53
#Mann= 5 ,-1,0
       0      .1       0      10     .06       0   74.92    .045       0
    96.1     .06       0     100      .1       0
#XS Ineff= 2 , 0
           66.29 2399.76  193.31          2402.4
Permanent Ineff=
       F       F
Bank Sta=74.92,96.1
XS Rating Curve= 0 ,0
Exp/Cntr(USF)=0,0
Exp/Cntr=0.3,0.1

Type RM Length L Ch R = 1 ,2761    ,246.1,253.1,256.4
XS GIS Cut Line= 2
2267075.72291914598966.7251992452267066.01560081599355.017932634
#Sta/Elev= 30
       0  2398.6    18.5 2390.28    22.5 2386.91    26.5 2385.13    42.5 2385.09
    46.5 2385.47    54.5 2387.55    58.5 2387.56    94.5 2386.26   102.5 2385.53
   158.5 2384.03   186.5 2382.69   194.5 2384.06   202.5 2382.38   222.5 2382.66
   238.5 2383.46   257.4 2380.81   266.5  2379.7   278.5 2379.96   279.92380.794
   282.5 2382.38   286.5 2387.51   290.5 2390.69   298.5 2393.05   314.6 2399.77
   334.6 2410.66   342.6  2413.5   354.6  2419.2   374.6 2429.86   388.4 2435.45
#Mann= 4 ,-1,0
       0     .06       0      70      .1       0   257.4    .045       0
   279.9      .1       0
#XS Ineff= 2 , 0
          210.82 2387.68
Permanent Ineff=
       F       F
Bank Sta=257.4,279.9
XS Rating Curve= 0 ,0
Exp/Cntr(USF)=0,0
Exp/Cntr=0.3,0.1

Type RM Length L Ch R = 1 ,2508    ,249.7,246.4,244.8
XS GIS Cut Line= 4
2266940.79724538 598883.270932232266904.27881061599011.570053883
2266816.07155222599186.3335621662266839.81876103599357.314243237
#Sta/Elev= 30
       0 2419.12    10.3 2414.34    26.9 2408.35    35.3 2404.23    53.8 2393.04
    72.7    2384    79.7 2382.06   110.1 2381.51   135.2 2379.16   162.1 2378.42
   179.3 2376.62     189 2378.88   206.1 2376.91   224.8 2377.08   232.9 2375.55
  238.03 2372.08   247.2 2371.03  257.812372.078   269.6 2376.48   283.1 2375.33
   296.5  2376.3   307.4 2374.99   320.1 2374.65   323.4 2375.41     332 2381.27
   352.2 2383.15   372.4 2386.62   420.4 2401.33   473.4 2414.45   501.8 2422.33
#Mann= 5 ,-1,0
       0      .1       0      50     .06       0   153.4      .1       0
  238.03    .045       0  257.81      .1       0
Bank Sta=238.03,257.81
XS Rating Curve= 0 ,0
Exp/Cntr(USF)=0,0
Exp/Cntr=0.3,0.1

Type RM Length L Ch R = 1 ,2261    ,247.4,251.4,256.1
XS GIS Cut Line= 3
2266656.80994121598880.053341161 2266572.1205796599241.181562337
2266592.89344188599328.267792665
#Sta/Elev= 30
       0 2393.25     9.4 2387.23    34.7  2373.7    61.4 2374.43   112.1 2371.29
   167.9 2370.63   173.7 2370.12   181.9 2367.09   194.3 2365.49  196.62 2364.26
   198.4 2363.46   206.6 2362.74   210.7 2362.74   214.5 2364.27   218.9 2366.92
   227.1 2368.22   237.8 2367.58   247.7 2366.16     260 2366.55   268.2 2367.79
   276.4 2366.96   284.6 2367.38   301.1  2366.5   309.3 2367.14   333.9 2366.24
   342.2 2369.24   354.2 2379.25   358.6 2381.35   420.3 2392.79   460.5 2401.79
#Mann= 4 ,-1,0
       0     .06       0      60      .1       0  196.62    .045       0
   214.5      .1       0
#XS Ineff= 2 , 0
                          227.39         2372.26
Permanent Ineff=
       F       F
Bank Sta=196.62,214.5
XS Rating Curve= 0 ,0
Exp/Cntr(USF)=0,0
Exp/Cntr=0.3,0.1

Type RM Length L Ch R = 1 ,2010    ,305.3,294.5,282.8
XS GIS Cut Line= 4
2266482.24581743598812.2393979142266437.28749981598907.818020519
 2266331.9547037599030.0560801922266354.05385877599250.847505694
#Sta/Elev= 30
       0 2393.59    18.7  2385.8    45.2 2378.29    62.9 2374.74    71.8 2371.76
      85 2371.66   132.9 2365.01   135.7 2363.39   141.4 2358.25  143.14 2357.49
   149.7 2356.76  162.222357.495   166.9 2359.01   170.8 2359.39   181.1 2359.69
   189.6 2358.82   205.4 2358.85   217.6 2360.18   228.9 2358.58   243.5 2359.01
   260.5 2357.22   278.2 2358.11   306.6 2357.37   322.4 2358.31   330.4 2356.98
   370.6 2358.25   394.7 2367.11     443 2371.93   467.1 2378.02   488.9 2382.52
#Mann= 5 ,-1,0
       0      .1       0      30     .06       0  135.62      .1       0
  143.14    .045       0  162.22      .1       0
#XS Ineff= 2 , 0
                          214.99         2366.14
Permanent Ineff=
       F       F
Bank Sta=143.14,162.22
XS Rating Curve= 0 ,0
Exp/Cntr(USF)=0,0
Exp/Cntr=0.3,0.1

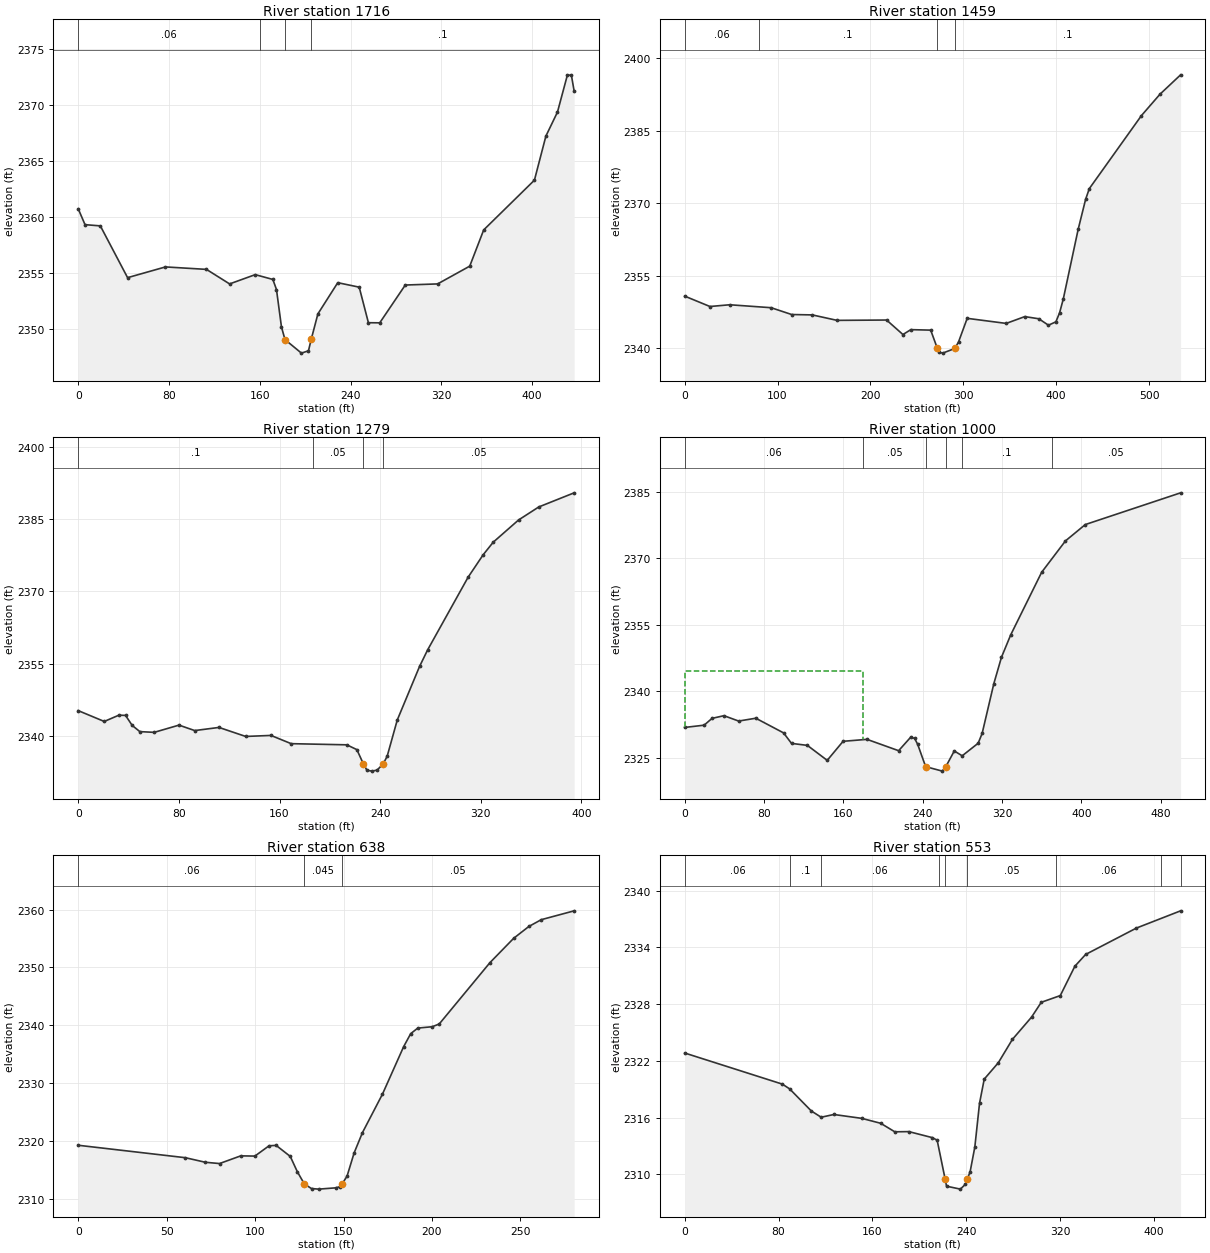
Type RM Length L Ch R = 1 ,1716    ,249.5,256.9,255.2
XS GIS Cut Line= 4
2266172.64245883598778.5858984852266143.88003414 598916.00637203
2266192.61636487598995.1030399422266228.56939574599195.641056569
#Sta/Elev= 30
       0 2360.75       6 2359.33    19.5 2359.22    43.5 2354.59    76.9 2355.55
     113 2355.33   133.4 2354.03     156 2354.86   171.5 2354.43   174.7 2353.53
   179.1 2350.18   182.2 2349.05   196.7 2347.84   202.9 2348.05  205.28 2349.06
   211.2 2351.35   228.7 2354.14   247.6 2353.74   255.7 2350.56   265.7 2350.55
   288.2 2353.93   316.7 2354.03     345 2355.62   357.3 2358.86     402 2363.31
   412.1 2367.25   422.3  2369.4   431.1 2372.73   434.6 2372.67     437 2371.28
#Mann= 4 ,-1,0
       0     .06       0   160.4      .1       0   182.2    .045       0
  205.28      .1       0
Bank Sta=182.2,205.28
XS Rating Curve= 0 ,0
Exp/Cntr(USF)=0,0
Exp/Cntr=0.3,0.1

Type RM Length L Ch R = 1 ,1459    ,175.8,179.1,182.9
XS GIS Cut Line= 4
2266024.95641268598761.576140906 2265924.8405659598967.859424782
2265974.25595173599097.8999137962265968.02713509599263.407051564
#Sta/Elev= 30
       0 2350.75    27.2  2348.6    48.5 2348.96    93.1 2348.35   115.2 2346.94
   137.4 2346.86   164.1 2345.73   217.4  2345.8     235  2342.8   243.5 2343.81
   264.9 2343.71   272.12339.908   273.5 2339.18   277.8 2338.95   290.92339.913
   294.9 2341.28   304.2 2346.15   346.2  2345.1   366.2 2346.51   381.3 2346.06
   391.7 2344.73   399.7 2345.43   403.7  2347.3   407.7 2350.19   423.7 2364.58
   431.7 2370.78   435.7    2373   491.8 2388.11   511.8 2392.54     534 2396.55
#Mann= 4 ,-1,0
       0     .06       0      80      .1       0   272.1    .045       0
   290.9      .1       0
Bank Sta=272.1,290.9
XS Rating Curve= 0 ,0
Exp/Cntr(USF)=0,0
Exp/Cntr=0.3,0.1

Type RM Length L Ch R = 1 ,1279    ,280.2,279.5,276.6
XS GIS Cut Line= 3
2265865.04430584598876.8575161952265788.34450665598964.742702764
2265763.57686317599241.181562337
#Sta/Elev= 30
       0 2345.25    20.7    2343    32.3  2344.3    37.6 2344.26    42.9 2342.18
      49 2340.89    60.4 2340.74    80.1 2342.24    92.6 2341.11   111.9 2341.76
   133.1 2339.89   153.2  2340.1   169.3 2338.39   213.5 2338.15   221.5 2337.15
   226.6 2334.23   229.5 2332.87   233.6 2332.69   237.6 2332.91   242.5 2334.22
   245.6  2335.8   253.6  2343.3   271.3 2354.41   277.7 2357.84   309.9 2372.94
   321.9 2377.61   329.9 2380.22     350 2384.82   366.1 2387.53   394.2 2390.46
#Mann= 4 ,-1,0
       0      .1       0  186.65     .05       0   226.6    .045       0
   242.5     .05       0
Bank Sta=226.6,242.5
XS Rating Curve= 0 ,0
Exp/Cntr(USF)=0,0
Exp/Cntr=0.3,0.1

Type RM Length L Ch R = 1 ,1000    ,361.6,361.8,361.4
XS GIS Cut Line= 2
2265507.17331455598757.5875000562265528.24035684599257.143482634
#Sta/Elev= 30
       0  2331.8    19.6 2332.31    27.6 2333.85    39.6 2334.45    54.4 2333.24
    71.7 2333.88    99.7 2330.57   107.7  2328.2   123.7 2327.75   143.7 2324.37
   159.7 2328.67   183.8 2329.11   215.7 2326.55   227.8 2329.58   231.8 2329.34
   234.9 2327.99  242.942322.951   259.8 2321.94  263.282322.951   271.8 2326.49
   279.8  2325.4   295.9 2328.24   299.9 2330.45   311.7  2341.7   319.4 2347.65
   328.7 2352.69   359.9 2366.82   383.9  2373.9   403.9 2377.59     500 2384.75
#Mann= 6 ,-1,0
       0     .06       0     180     .05       0  242.94    .045       0
  263.28     .05       0     280      .1       0     370     .05       0
#XS Ineff= 2 , 0
          179.42 2344.62
Permanent Ineff=
       F       F
Bank Sta=242.94,263.28
XS Rating Curve= 0 ,0
Exp/Cntr(USF)=0,0
Exp/Cntr=0.3,0.1

Type RM Length L Ch R = 1 ,638     ,84.6,85.5,86.9
XS GIS Cut Line= 4
2265198.09618956598919.0085892342265154.08967978598964.956562685
2265161.85553445599105.389101261 2265225.2766809599147.454147378
#Sta/Elev= 30
       0 2319.28    60.6 2317.13    71.9 2316.34    79.9 2316.12    91.9 2317.45
    99.9 2317.41   107.9 2319.19   111.9 2319.26   119.9 2317.35   123.9  2314.7
   127.9 2312.57   131.9  2311.8     136  2311.7   145.5 2311.92     148 2312.12
  149.14 2312.57     152 2313.94     156 2317.96   160.7 2321.46     172  2328.1
     184 2336.32     188 2338.57     192 2339.53   200.1 2339.76   204.1 2340.23
   232.8 2350.84   246.2 2355.04   254.8 2357.09   261.8 2358.26   280.4 2359.79
#Mann= 3 ,-1,0
       0     .06       0   127.9    .045       0  149.14     .05       0
Bank Sta=127.9,149.14
XS Rating Curve= 0 ,0
Exp/Cntr(USF)=0,0
Exp/Cntr=0.3,0.1

Type RM Length L Ch R = 1 ,553     ,71.6,71.6,71.6
XS GIS Cut Line= 5
2265169.25333522 598855.224983382265080.70881873598930.608241511
2265072.88608368599041.8304069122265068.35185219599109.843879201
2265114.29167894599227.774435446
#Sta/Elev= 30
       0 2322.84    83.2 2319.55    89.4 2319.05   107.9 2316.71   116.3 2316.05
   127.1 2316.34   150.9 2315.93     167 2315.41     179 2314.51     191 2314.53
   211.1 2313.89   215.1 2313.62  221.892309.516   223.1 2308.76   234.9 2308.45
   239.2 2308.97  240.852309.519   243.2  2310.3   247.2 2312.91   251.2 2317.53
   255.2 2320.08   267.2 2321.81   279.2 2324.28   295.5 2326.63   303.8  2328.2
     320 2328.91   332.4 2332.01   341.6 2333.26   384.9 2336.05   422.5 2337.87
#Mann= 9 ,-1,0
       0     .06       0      90      .1       0  116.29     .06       0
  216.29     .05       0  221.89    .045       0  240.85     .05       0
  315.95     .06       0  405.95     .05       0  422.51     .06       0
Bank Sta=221.89,240.85
XS Rating Curve= 0 ,0
Exp/Cntr(USF)=0,0
Exp/Cntr=0.3,0.1

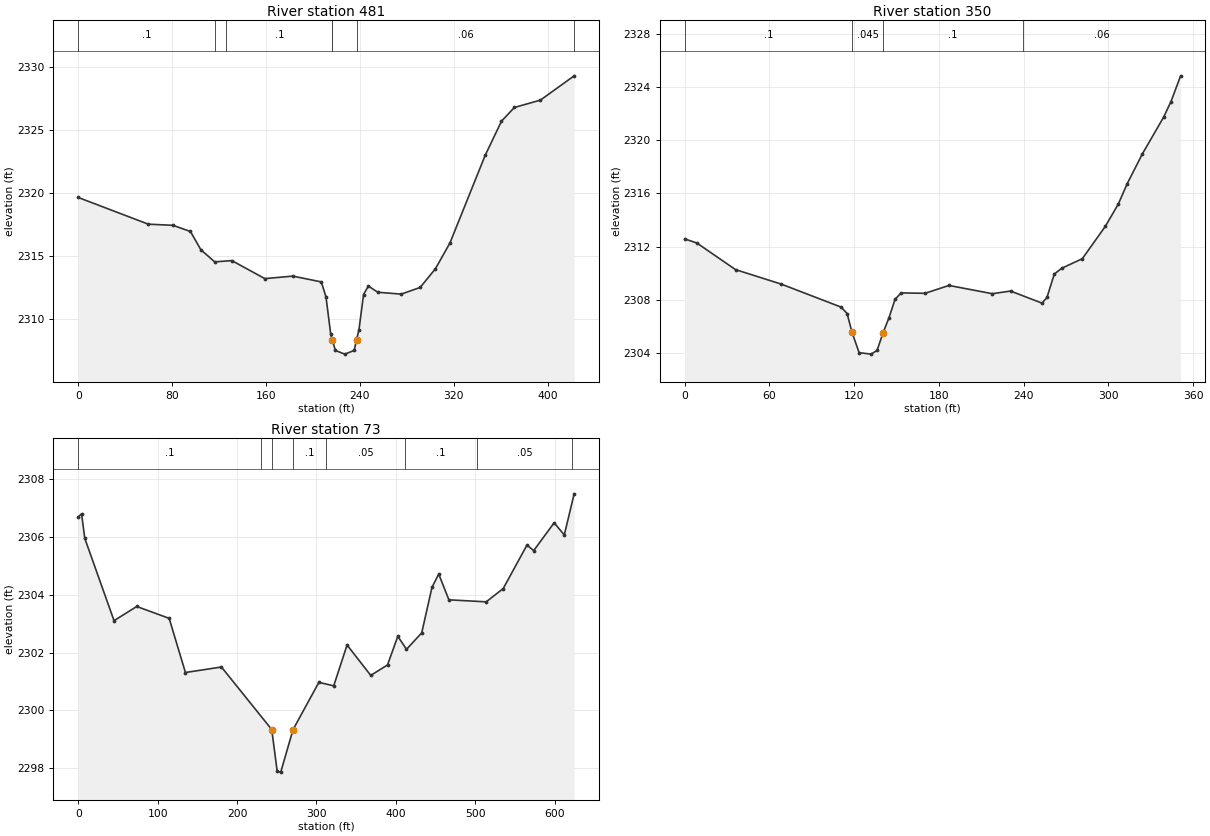
Type RM Length L Ch R = 1 ,481     ,135.6,131.2,127.1
XS GIS Cut Line= 5
2265097.60128211 598855.224983382265009.05676562598930.608241511
2265001.23403057599041.8304069122264996.69979908599109.843879201
2265042.63962583599227.774435446
#Sta/Elev= 30
       0 2319.65    59.7 2317.53    80.7 2317.44    95.6 2316.95   104.5  2315.5
   116.3 2314.54   130.9 2314.64     159 2313.21   182.8 2313.41   207.1 2312.95
   211.1 2311.76   215.1 2308.82   216.52308.338   219.1 2307.51   227.1 2307.22
   235.1 2307.51  237.092308.337   239.2 2309.17   243.1 2311.95   247.2 2312.62
   255.2 2312.13   275.2 2311.98   291.3 2312.51   304.3 2313.99   316.7 2316.04
   346.7 2322.99   360.6  2325.7   371.6 2326.79   393.7 2327.37   422.5  2329.3
#Mann= 7 ,-1,0
       0      .1       0  116.29     .06       0  126.29      .1       0
  216.29     .06       0   216.5    .045       0  237.09     .06       0
  422.51     .05       0
Bank Sta=216.5,237.09
XS Rating Curve= 0 ,0
Exp/Cntr(USF)=0,0
Exp/Cntr=0.3,0.1

Type RM Length L Ch R = 1 ,350     ,272.7,277.4,280.5
XS GIS Cut Line= 4
2264963.71410345598999.9722240982264867.17794291599052.265720174
2264907.01704686599164.8704265622265001.50161198599241.881818684
#Sta/Elev= 30
       0 2312.59     8.6 2312.28      36 2310.28    68.4 2309.19   110.8 2307.46
     115 2306.98  118.45 2305.57   123.5 2304.04     132 2303.93   136.2 2304.21
   140.5 2305.55   144.7 2306.68   148.9 2308.04   153.2 2308.53   170.2  2308.5
   187.1 2309.09   217.8 2308.47   230.7 2308.67     253 2307.76   256.5  2308.2
   261.7 2309.95   266.9 2310.38   281.5  2311.1   297.8 2313.53     307 2315.21
   313.3 2316.74   324.1 2318.99   339.1 2321.74   344.3 2322.91   351.1 2324.84
#Mann= 4 ,-1,0
       0      .1       0  118.45    .045       0   140.5      .1       0
  239.23     .06       0
Bank Sta=118.45,140.5
XS Rating Curve= 0 ,0
Exp/Cntr(USF)=0,0
Exp/Cntr=0.3,0.1

Type RM Length L Ch R = 1 ,73      ,,,
XS GIS Cut Line= 4
 2264836.2965992599052.0560287332264603.40193714599100.539470373
 2264604.4687385599154.4971901592264915.83770194599271.397173546
#Sta/Elev= 30
       0 2306.68     4.2 2306.79     8.3 2305.94    45.1  2303.1    73.7 2303.59
   114.5 2303.18     135 2301.31   180.3  2301.5  243.67 2299.34   250.5  2297.9
     255 2297.87   270.5 2299.34     303 2300.97   321.7 2300.85   338.5 2302.26
   368.3 2301.21   389.4 2301.57   402.4 2302.56   413.3 2302.11   432.5 2302.68
   445.4 2304.25   453.9 2304.71   466.7 2303.82   513.7 2303.75   535.1 2304.21
     565 2305.71   573.5 2305.52   599.2 2306.48     612 2306.06   624.4 2307.48
#Mann= 8 ,-1,0
       0      .1       0     230     .05       0  243.67    .045       0
   270.5      .1       0  311.86     .05       0  411.86      .1       0
  501.86     .05       0  621.86     .06       0
Bank Sta=243.67,270.5
XS Rating Curve= 0 ,0
Exp/Cntr(USF)=0,0
Exp/Cntr=0.3,0.1
LCMann Table=0

Chan Stop Cuts=-1
Use User Specified Reach Order=0
Composite Channel Slope=5